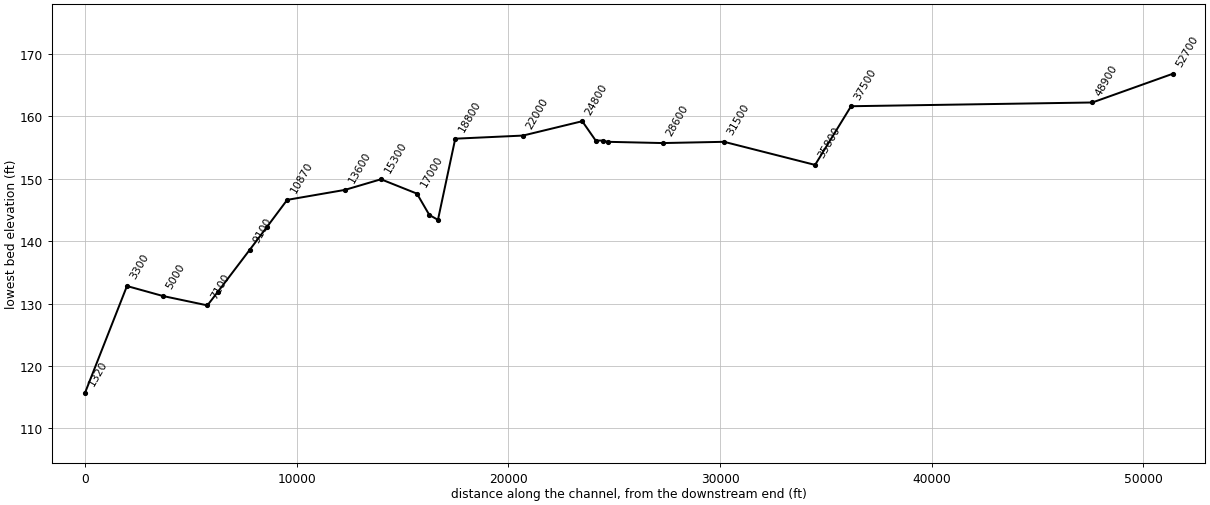
--- CCR_Saluda.prj (project) ---

Proj Title=CCR_Saluda
Current Plan=p04
Default Exp/Contr=0.3,0.1
English Units
Geom File=g01
Geom File=g03
Flow File=f01
Plan File=p02
Plan File=p04
Y Axis Title=Elevation
X Axis Title(PF)=Main Channel Distance
X Axis Title(XS)=Station
BEGIN DESCRIPTION:
CCR_Saluda
END DESCRIPTION:
DSS Export Rating Curves= 0
DSS Export Rating Curve Sorted= 0
DSS Export Volume Flow Curves= 0
DXF OffsetX= 0
DXF OffsetY= 0
DXF ScaleX= 1
DXF ScaleY= 10

--- CCR_Saluda.p04 (plan) ---

Plan Title=Corrected EffectiveNAVD88
Program Version=5.03
Short Identifier=CE88
Geom File=g03
Flow File=f01
Subcritical Flow
K Sum by GR= 0
Std Step Tol= 0.01
Critical Tol= 0.01
Num of Std Step Trials= 20
Max Error Tol= 0.3
Flow Tol Ratio= 0.001
Split Flow NTrial= 30
Split Flow Tol= 0.02
Split Flow Ratio= 0.02
Log Output Level= 0
Friction Slope Method= 1
Unsteady Friction Slope Method= 2
Unsteady Bridges Friction Slope Method= 1
Parabolic Critical Depth
Global Vel Dist= 0 , 0 , 0
Global Log Level= 0
CheckData=True
Encroach Param=-1 ,0,0, 0
Computation Interval=1HOUR
Output Interval=1HOUR
Instantaneous Interval=1HOUR
Mapping Interval=1HOUR
Run HTab= 0
Run UNet= 0
Run Sediment= 0
Run PostProcess= 0
Run WQNet= 0
Run RASMapper= 0
UNET Theta= 1
UNET Theta Warmup= 1
UNET ZTol= 0.02
UNET ZSATol= 0.05
UNET MxIter= 20
UNET Max Iter WO Improvement= 0
UNET MaxInSteps= 0
UNET DtIC= 0
UNET DtMin= 0
UNET MaxCRTS= 20
UNET WFStab= 2
UNET SFStab= 1
UNET WFX= 1
UNET SFX= 1
UNET DSS MLevel= 4
UNET Pardiso=0
UNET DZMax Abort= 100
UNET Use Existing IB Tables=-1
UNET Froude Reduction=False
UNET Froude Limit= 1
UNET Froude Power= 10
UNET Time Slicing=0,0, 5
UNET D1 Cores= 0
UNET D2 Coriolis=0
UNET D2 Cores= 0
UNET D2 Theta= 1
UNET D2 Theta Warmup= 1
UNET D2 Z Tol= 0.01
UNET D2 Volume Tol= 0.01
UNET D2 Max Iterations= 20
UNET D2 Equation= 0
UNET D2 RampUpFraction=0.1
UNET D2 TimeSlices= 1
UNET D2 BCVolumeCheck=0
UNET D1D2 MaxIter= 0
UNET D1D2 ZTol=0.01
UNET D1D2 QTol=0.1
UNET D1D2 MinQTol=1
Write IC File= 0
Write IC File at Fixed DateTime=0
Write IC File at Sim End=0
Echo Input=False
Echo Parameters=False
Echo Output=False
Write Detailed= 0
HDF Write Warmup=0
HDF Write Time Slices=0
HDF Flush=0
HDF Face Node Velocities=0
HDF Compression= 1
HDF Chunk Size= 1
HDF Spatial Parts= 1
HDF Use Max Rows=0
HDF Fixed Rows= 1
Calibration Method= 0
Calibration Iterations= 20
Calibration Max Change=0.05
Calibration Tolerance=0.2
Calibration Maximum=1.5
Calibration Minimum=0.5
Calibration Optimization Method= 1
WQ AD Non Conservative
WQ ULTIMATE=-1
WQ Max Comp Step=1HOUR
WQ Output Interval=15MIN
WQ Output Selected Increments= 0
WQ Output face flow=0
WQ Output face velocity=0
WQ Output face area=0
WQ Output face dispersion=0
WQ Output cell volume=0
WQ Output cell surface area=0
WQ Output cell continuity=0
WQ Output cumulative cell continuity=0
WQ Output face conc=0
WQ Output face dconc_dx=0
WQ Output face courant=0
WQ Output face peclet=0
WQ Output face adv mass=0
WQ Output face disp mass=0
WQ Output cell mass=0
WQ Output cell source sink temp=0
WQ Output nsm pathways=0
WQ Output nsm derived pathways=0
WQ Output MaxMinRange=-1
WQ Daily Max Min Mean=-1
WQ Daily Range=0
WQ Daily Time=0
WQ Create Restart=0
WQ Fixed Restart=0
WQ System Summary=0
WQ Write To DSS=0
WQ Use Fixed Temperature=0
Sorting and Armoring Iterations= 10
XS Update Threshold= 0.02
Bed Roughness Predictor= 0
Hydraulics Update Threshold= 0.02
Energy Slope Method= 1
Volume Change Method= 0
Sediment Retention Method= 0
XS Weighting Method= 0
Number of US Weighted Cross Sections= 1
Number of DS Weighted Cross Sections= 1
Upstream XS Weight=0.25
Main XS Weight=0.5
Downstream XS Weight=0.25
Number of DS XS's Weighted with US Boundary= 1
Upstream Boundary Weight= 1
Weight of XSs Associated with US Boundary= 0
Number of US XS's Weighted with DS Boundary= 1
Downstream Boundary Weight= 0.5
Weight of XSs Associated with DS Boundary= 0.5
Percentile Method= 0
Sediment Output Level= 4
Mass or Volume Output= 0
Output Increment Type= 1
Profile and TS Output Increment= 10
XS Output Flag= 0
XS Output Increment= 10
Write Gradation File= 0
Read Gradation Hotstart= 0
Write HDF5 File= 1
Write DSS Sediment File= 0
SV Curve= 0
Specific Gage Flag= 0

--- CCR_Saluda.p02 (plan) ---

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Plan Title=Duplicate Effective
Short Identifier=DE
Geom File=g01
Flow File=f01

--- CCR_Saluda.f01 (steady flow) ---

Flow Title=CCR_Saluda
Program Version=5.03
Number of Profiles= 5
Profile Names=10 Year,50 Year,100 Year,FW,500 Year
River Rch & RM=Saluda River,Saluda River    ,52700
   32000   90000  105000  105000  145000
Boundary for River Rch & Prof#=Saluda River,Saluda River    , 1
Up Type= 0
Dn Type= 3
Dn Slope=0.002
Boundary for River Rch & Prof#=Saluda River,Saluda River    , 2
Up Type= 0
Dn Type= 3
Dn Slope=0.002
Boundary for River Rch & Prof#=Saluda River,Saluda River    , 3
Up Type= 0
Dn Type= 3
Dn Slope=0.002
Boundary for River Rch & Prof#=Saluda River,Saluda River    , 4
Up Type= 0
Dn Type= 3
Dn Slope=0.002
Boundary for River Rch & Prof#=Saluda River,Saluda River    , 5
Up Type= 0
Dn Type= 3
Dn Slope=0.002
DSS Import GetInterval= 0
DSS Import GetPeak= 0
DSS Import FillOption= 0

--- CCR_Saluda.g03 (geometry) ---

Geom Title=CCR_Corrected_Effective_SaludaNAVD88
Program Version=5.03

River Reach=Saluda River    ,Saluda River
Reach XY= 2
0.251626898047720.985900216919740.251626898047720.01518438177874

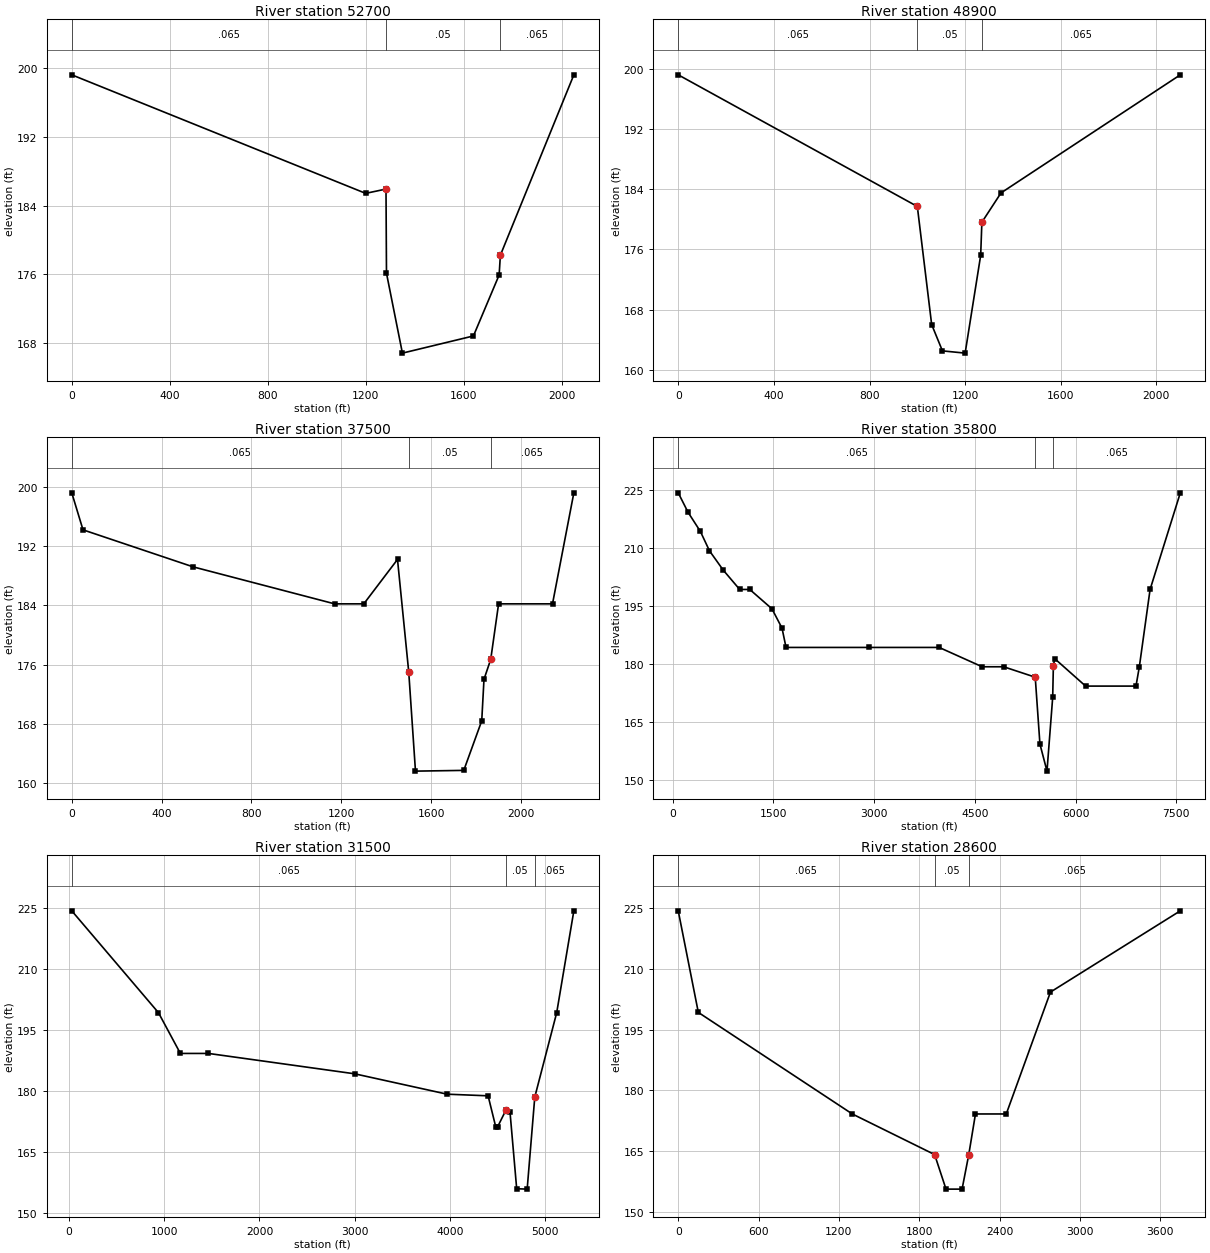
Type RM Length L Ch R = 1 ,52700   ,3800,3800,3800
BEGIN DESCRIPTION:
END
END DESCRIPTION:
#Sta/Elev= 9
       0  199.22    1200  185.42    1283  185.92    1285  176.12    1350  166.82
    1640  168.82    1745  175.92    1750  178.22    2050  199.22
#Mann= 3 , 0 , 0
       0    .065       0    1283     .05       0    1750    .065       0
Bank Sta=1283,1750
XS Rating Curve= 0 ,0
Exp/Cntr=0.3,0.1

Type RM Length L Ch R = 1 ,48900   ,11400,11400,11400
#Sta/Elev= 9
       0  199.22    1000  181.72    1060  166.02    1105  162.52    1200  162.22
    1265  175.22    1270  179.62    1350  183.52    2100  199.22
#Mann= 3 , 0 , 0
       0    .065       0    1000     .05       0    1270    .065       0
Bank Sta=1000,1270
XS Rating Curve= 0 ,0
Exp/Cntr=0.3,0.1

Type RM Length L Ch R = 1 ,37500   ,1700,1700,1700
BEGIN DESCRIPTION:
FEMA XS: O
END DESCRIPTION:
#Sta/Elev= 15
       0  199.22      50  194.22     540  189.22    1170  184.22    1300  184.22
    1450  190.22    1500  175.02    1530  161.62    1745  161.72    1825  168.42
    1835  174.02    1865  176.72    1900  184.22    2140  184.22    2235  199.22
#Mann= 3 , 0 , 0
       0    .065       0    1500     .05       0    1865    .065       0
Bank Sta=1500,1865
XS Rating Curve= 0 ,0
Exp/Cntr=0.3,0.1

Type RM Length L Ch R = 1 ,35800   ,4100,4300,4400
BEGIN DESCRIPTION:
FEMA XS: N
END DESCRIPTION:
#Sta/Elev= 25
      85  224.22     230  219.22     415  214.22     550  209.22     755  204.22
    1000  199.22    1150  199.22    1480  194.22    1630  189.22    1690  184.22
    2930  184.22    3970  184.22    4610  179.22    4930  179.22    5400  176.52
    5470  159.22    5575  152.22    5660  171.32    5670  179.42    5690  181.32
    6150  174.22    6900  174.22    6950  179.22    7110  199.22    7560  224.22
#Mann= 3 , 0 , 0
      85    .065       0    5400     .05       0    5670    .065       0
Bank Sta=5400,5670
XS Rating Curve= 0 ,0
Exp/Cntr=0.3,0.1

Type RM Length L Ch R = 1 ,31500   ,2900,2900,2900
BEGIN DESCRIPTION:
FEMA XS: M
END DESCRIPTION:
#Sta/Elev= 16
      30  224.22     940  199.22    1170  189.22    1465  189.22    3000  184.22
    3970  179.22    4400  178.82    4480  171.22    4500  171.22    4585  175.22
    4630  174.82    4700  156.02    4810  155.92    4890  178.52    5120  199.22
    5300  224.22
#Mann= 3 , 0 , 0
      30    .065       0    4585     .05       0    4890    .065       0
Bank Sta=4585,4890
XS Rating Curve= 0 ,0
Exp/Cntr=0.3,0.1

Type RM Length L Ch R = 1 ,28600   ,2600,2600,2600
BEGIN DESCRIPTION:
FEMA XS: L
END DESCRIPTION:
#Sta/Elev= 11
       0  224.22     150  199.22    1300  174.22    1915  164.22    2000  155.72
    2120  155.72    2170  164.22    2220  174.22    2450  174.22    2780  204.22
    3750  224.22
#Mann= 3 , 0 , 0
       0    .065       0    1915     .05       0    2170    .065       0
Bank Sta=1915,2170
XS Rating Curve= 0 ,0
Exp/Cntr=0.3,0.1

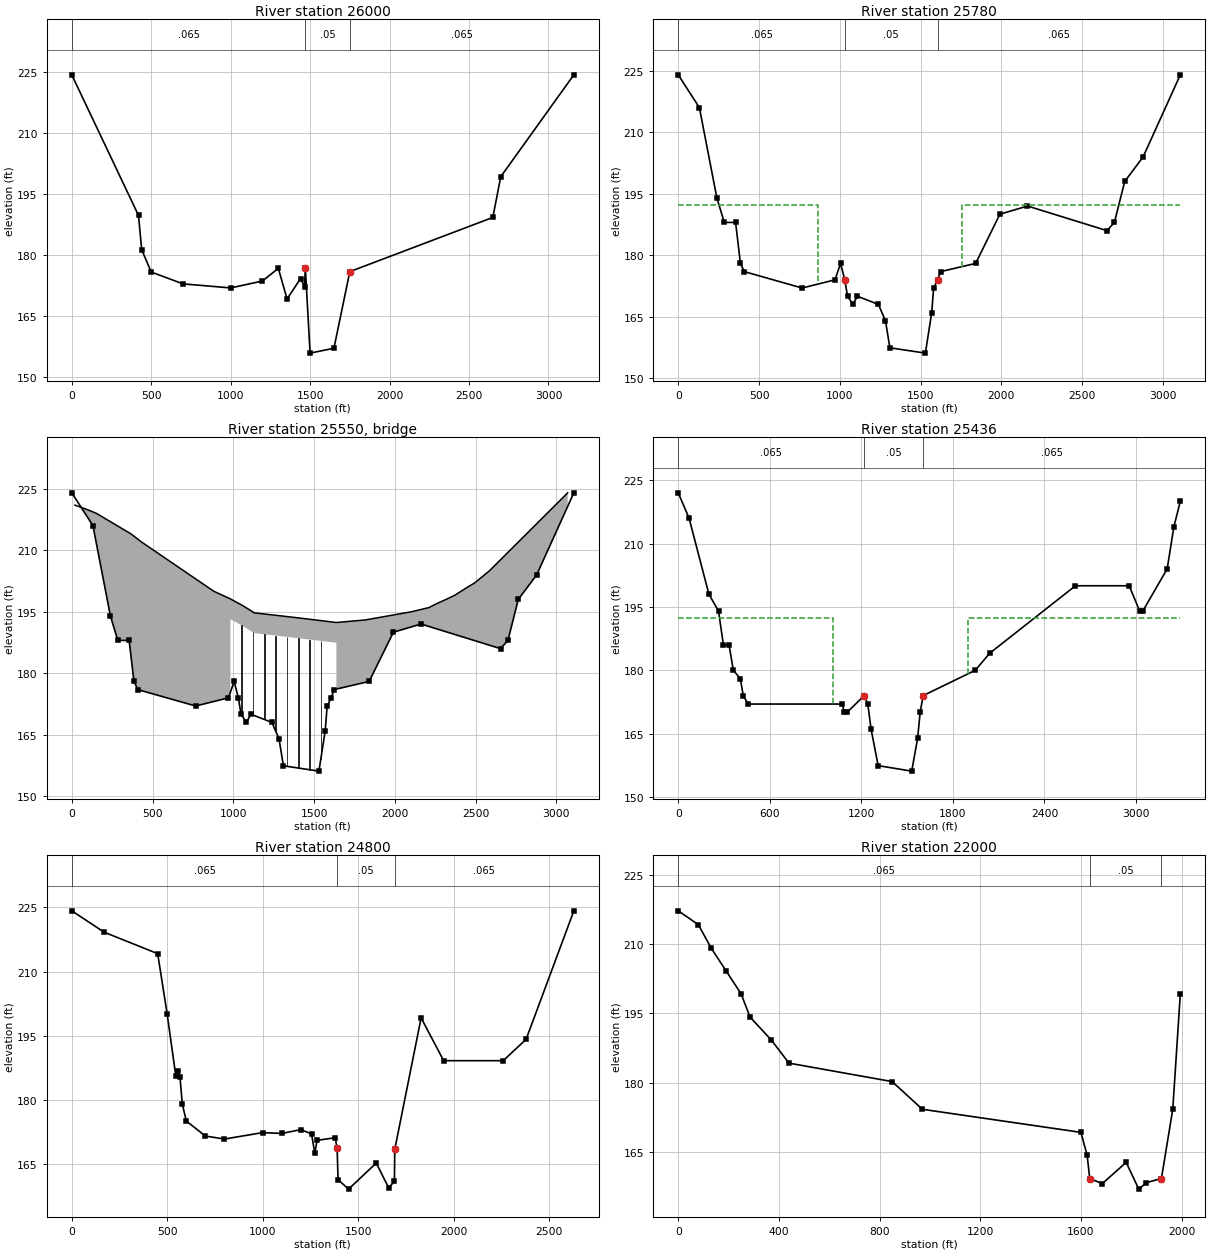
Type RM Length L Ch R = 1 ,26000   ,320,220,170
BEGIN DESCRIPTION:
FEMA XS: K
END DESCRIPTION:
#Sta/Elev= 18
       0  224.22     420  189.72     440  181.32     500  175.82     700  172.92
    1000  171.92    1200  173.62    1300  176.72    1355  169.22    1440  174.22
    1465  172.22    1470  176.82    1500  155.92    1650  157.12    1750  175.92
    2650  189.22    2700  199.22    3160  224.22
#Mann= 3 , 0 , 0
       0    .065       0    1470     .05       0    1750    .065       0
Bank Sta=1470,1750
XS Rating Curve= 0 ,0
Exp/Cntr=0.5,0.3

Type RM Length L Ch R = 1 ,25780   ,344,344,344
BEGIN DESCRIPTION:
New Section US I-20
END DESCRIPTION:
#Sta/Elev= 30
       0     224     131     216     239     194     285     188     355     188
     385     178     409     176     767     172     970     174    1005     178
    1031     174    1048     170    1081     168    1109     170    1239     168
    1283     164    1310  157.42    1530  156.12    1569     166    1581     172
    1606     174    1624     176    1841     178    1991     190    2162     192
    2654     186    2700     188    2764     198    2878     204    3108     224
#Mann= 3 , 0 , 0
       0    .065       0    1031     .05       0    1606    .065       0
#XS Ineff= 2 , 0
       0   866.1  192.37  1753.8       0  192.37
Permanent Ineff=
       F       F
Bank Sta=1031,1606
XS Rating Curve= 0 ,0
Exp/Cntr=0.5,0.3

Type RM Length L Ch R = 3 ,25550   ,,,
Bridge Culvert--1,0,-1,-1, 0
Deck Dist Width WeirC Skew NumUp NumDn MinLoCord MaxHiCord MaxSubmerge Is_Ogee
95,108,2.5,0, 25, 26, 191.32, , 0.98, 0, 5.8,5.8,,
    19.5    90.2     152     366     399     432     879     982     982    1061
    1130    1391    1638    1638  1817.7    2104    2210    2260    2317    2370
    2410    2450    2493    2586    3070
     221     220     219     214     213     212     200 198.123 198.123 196.426
  194.73  193.55  192.37  192.37     193     195     196     197     198     199
     200     201     202     205     224
                                                                 193.173 191.476
  189.78   188.6  187.42
                                        
       0   167.5   238.2     300     514     547     580    1027    1130    1130
    1209    1278    1539    1786    1786  1965.7    2252    2358    2408    2465
    2518    2558    2598    2641    2734    3218
     222     221     220     219     214     213     212     200 198.123 198.123
 196.426  194.73  193.55  192.37  192.37     193     195     196     197     198
     199     200     201     202     205     224
                                                                         193.173
 191.476  189.78   188.6  187.42
                                                
Pier Skew, UpSta & Num, DnSta & Num=  ,1052, 2 ,1200, 2 , 0 , 0 , 0 ,,
     3.5     3.5
   156.9   192.2
     3.5     3.5
   156.9   192.2
Pier Skew, UpSta & Num, DnSta & Num=  ,1122, 2 ,1270, 2 , 0 , 0 , 0 ,,
     3.5     3.5
   156.9   192.2
     3.5     3.5
   156.9   192.2
Pier Skew, UpSta & Num, DnSta & Num=  ,1192, 2 ,1340, 2 , 0 , 0 , 0 ,,
     3.5     3.5
   156.9   192.2
     3.5     3.5
   156.9   192.2
Pier Skew, UpSta & Num, DnSta & Num=  ,1262, 2 ,1410, 2 , 0 , 0 , 0 ,,
     3.5     3.5
   156.9 193.173
     3.5     3.5
   156.9   192.2
Pier Skew, UpSta & Num, DnSta & Num=  ,1332, 2 ,1480, 2 , 0 , 0 , 0 ,,
     3.5     3.5
   156.9   192.2
     3.5     3.5
   156.9   192.2
Pier Skew, UpSta & Num, DnSta & Num=  ,1402, 2 ,1550, 2 , 0 , 0 , 0 ,,
     3.5     3.5
   156.9   192.2
     3.5     3.5
   156.9   192.2
Pier Skew, UpSta & Num, DnSta & Num=  ,1472, 2 ,1620, 2 , 0 , 0 , 0 ,,
     3.5     3.5
   156.9   192.2
     3.5     3.5
   156.9   192.2
Pier Skew, UpSta & Num, DnSta & Num=  ,1542, 2 ,1690, 2 , 0 , 0 , 0 ,,
     3.5     3.5
   156.9   192.2
     3.5     3.5
   156.9   192.2
Abutment Skew #Up #Dn= , 3 , 3
     982     986    1020
 191.173 191.173 174.173
    1130    1134    1168
 191.173 191.173 174.173
Abutment Skew #Up #Dn= , 3 , 3
    1542    1634    1638
  139.42  185.42  185.42
    1692    1784    1786
  139.42  185.42  185.42
BR Coef= 0 , 0 , 1 ,1.25, 0 ,,,1.3,0,,2,191.42
WSPro=,,,, 1 ,,,, 0 ,,,, 0 ,,,,-1 ,-1 ,-1 , 0 , 0 , 0 , 0 , 0
BC Design=,, 0 ,, 0 ,,,,,,
BC Use User HTab Curves=0
BC User HTab FreeFlow(D)= 0

Type RM Length L Ch R = 1 ,25436   ,636,636,636
BEGIN DESCRIPTION:
New Section DS of I-20
END DESCRIPTION:
#Sta/Elev= 30
       0     222      71     216     201     198     264     194     296     186
     333     186     361     180     407     178     426     174     458     172
    1076     172    1087     170    1105     170    1219     174    1242     172
    1264     166    1310  157.42    1530  156.12    1569     164    1585     170
    1605     174    1947     180    2040     184    2603     200    2955     200
    3024     194    3044     194    3204     204    3248     214    3290     220
#Mann= 3 , 0 , 0
       0    .065       0    1219     .05       0    1605    .065       0
#XS Ineff= 2 , 0
       0  1014.1  192.37  1901.8       0  192.37
Permanent Ineff=
       F       F
Bank Sta=1219,1605
XS Rating Curve= 0 ,0
Exp/Cntr=0.5,0.3

Type RM Length L Ch R = 1 ,24800   ,2800,2800,2800
BEGIN DESCRIPTION:
FEMA XS: J
END DESCRIPTION:
#Sta/Elev= 30
       0  224.22     170  219.22     450  214.22     500  200.02     545  185.62
     555  186.82     567  185.32     579  179.12     600  175.12     700  171.62
     800  170.92    1000  172.42    1100  172.22    1200  173.12    1256  172.12
    1273  167.62    1285  170.62    1380  171.22    1390  168.72    1395  161.42
    1450  159.22    1595  165.32    1660  159.52    1690  161.02    1692  168.52
    1830  199.22    1948  189.22    2260  189.22    2380  194.22    2630  224.22
#Mann= 3 , 0 , 0
       0    .065       0    1390     .05       0    1692    .065       0
Bank Sta=1390,1692
XS Rating Curve= 0 ,0
Exp/Cntr=0.5,0.3

Type RM Length L Ch R = 1 ,22000   ,3200,3200,3200
BEGIN DESCRIPTION:
FEMA XS: I
END DESCRIPTION:
#Sta/Elev= 20
       0  217.22      80  214.22     130  209.22     190  204.22     250  199.22
     285  194.22     370  189.22     440  184.22     850  180.22     970  174.22
    1600  169.22    1625  164.22    1635  159.22    1685  158.12    1780  162.72
    1830  156.92    1860  158.32    1920  159.22    1965  174.22    1995  199.22
#Mann= 3 , 0 , 0
       0    .065       0    1635     .05       0    1920    .065       0
Bank Sta=1635,1920
XS Rating Curve= 0 ,0
Exp/Cntr=0.3,0.1

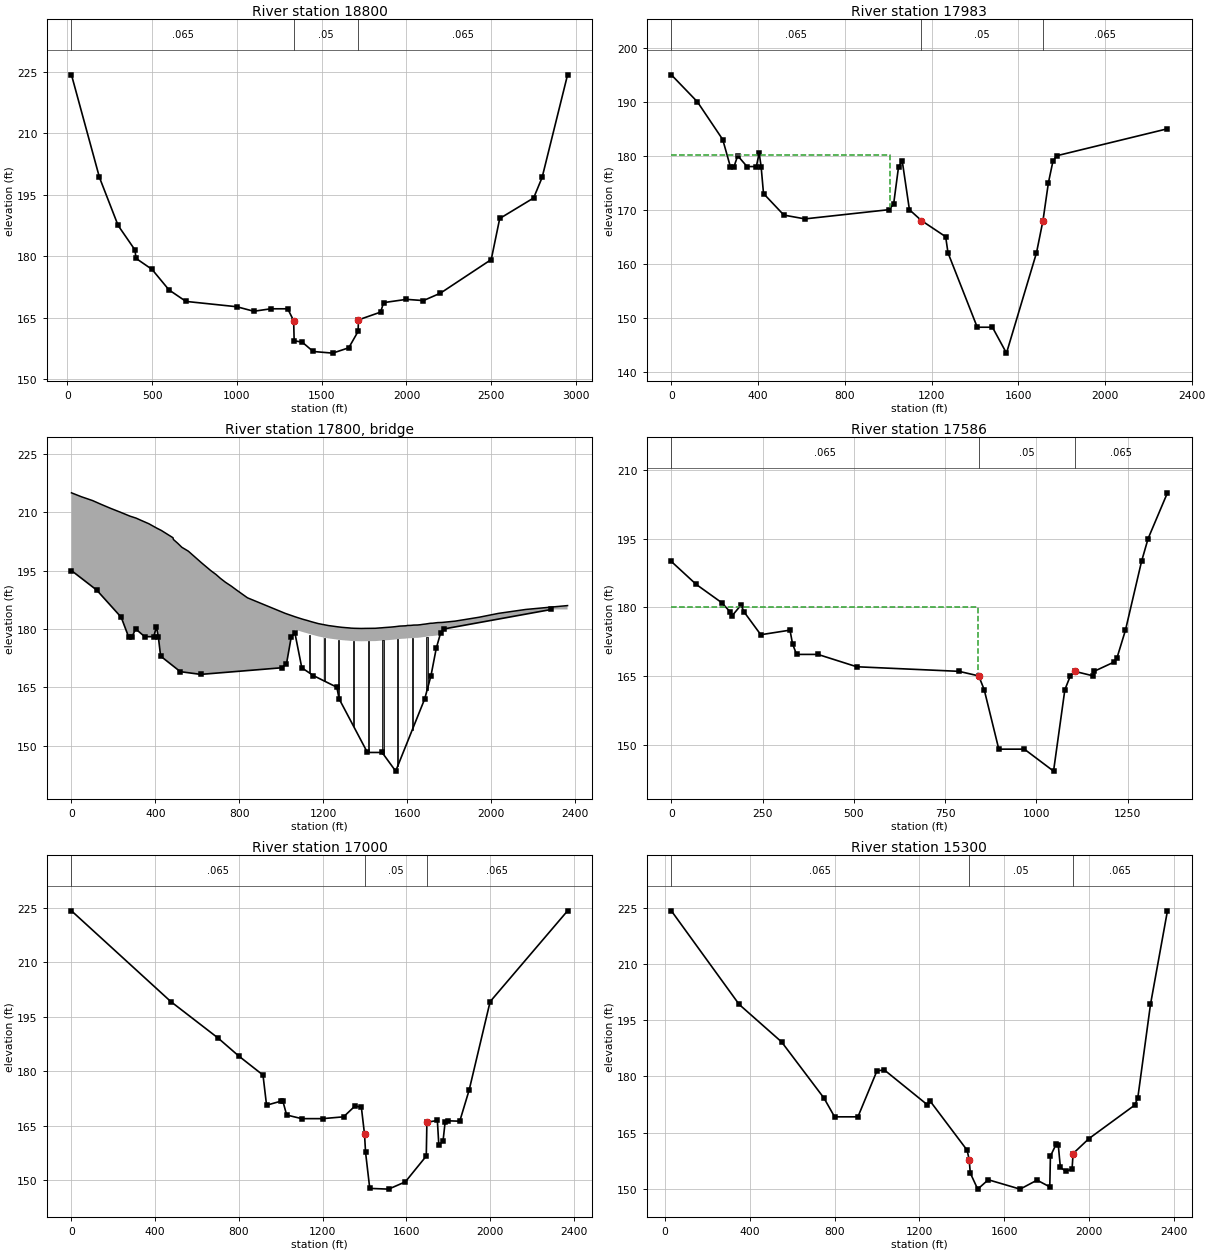
Type RM Length L Ch R = 1 ,18800   ,817,817,817
BEGIN DESCRIPTION:
FEMA XS: H
END DESCRIPTION:
#Sta/Elev= 30
      25  224.22     190  199.22     300  187.52     400  181.52     405  179.52
     500  176.82     600  171.82     700  169.02    1000  167.72    1100  166.62
    1200  167.22    1300  167.22    1335  164.32    1338  159.42    1385  159.12
    1450  156.82    1565  156.42    1660  157.72    1715  161.72    1717  164.52
    1848  166.42    1865  168.72    2000  169.52    2100  169.22    2200  171.02
    2500  179.22    2550  189.22    2750  194.22    2800  199.22    2950  224.22
#Mann= 3 , 0 , 0
      25    .065       0    1335     .05       0    1717    .065       0
Bank Sta=1335,1717
XS Rating Curve= 0 ,0
Exp/Cntr=0.5,0.3

Type RM Length L Ch R = 1 ,17983   ,407,407,407
#Sta/Elev= 30
       0     195     120     190     237     183     272     178     289     178
     306     180     349     178     392     178     405   180.5     414     178
     425     173     519     169     616   168.3    1002     170    1025     171
    1048     178    1065     179    1098     170    1153     168    1265     165
    1276     162  1410.8  148.22  1480.8  148.22  1545.6  143.42    1684     162
    1714     168    1739     175    1760     179    1777     180    2288     185
#Mann= 3 , 0 , 0
       0    .065       0    1153     .05       0    1714    .065       0
#XS Ineff= 2 , 0
       0    1010 180.115    1820       0 180.115
Permanent Ineff=
       F       F
Bank Sta=1153,1714
XS Rating Curve= 0 ,0
Exp/Cntr=0.5,0.3

Type RM Length L Ch R = 3 ,17800   ,,,
Bridge Culvert--1,0,-1,-1, 0
Deck Dist Width WeirC Skew NumUp NumDn MinLoCord MaxHiCord MaxSubmerge Is_Ogee
55,123,2.5,0, 77, 77, , , 0.98, 0, 7.5,7.5,,
       0      47     101     143     187     234     279     308     334     369
     405     428     484     486     507     526     557     578     599     620
     642     664     689     710     734     762     787     813     839     974
    1019    1065 1083.45 1104.65 1123.67 1142.94 1176.94 1199.82 1225.25    1251
 1267.33 1288.33 1305.41 1325.79    1332  1348.7 1381.56 1400.97 1447.82 1468.22
 1475.88 1488.341520.762 1533.511546.443 1565.65 1572.071591.275 1597.73 1604.19
 1616.83 1624.281631.7241637.273 1649.21 1662.05 1674.78 1687.39    1711 1721.69
 1745.221766.069    1829    1943    2036    2165    2365
     215     214     213     212     211     210     209 208.497  207.87 207.048
 205.965 205.336 203.447     203     202     201     200     199     198     197
     196     195     194     193     192     191     190     189     188     185
     184 183.136 182.811 182.456 182.175 181.861 181.361 181.122 180.859 180.673
  180.55 180.411 180.332 180.247   180.2 180.157 180.115 180.136 180.159 180.246
 180.268 180.331 180.459 180.521 180.598 180.726 180.743 180.791 180.839 180.887
 180.902 180.942 180.983  180.99     181  181.07  181.17  181.25 181.447 181.467
  181.62 181.659     182     183     184     185     186
                                                                                
                                                                                
                                                                                
         179.841 179.516 179.161  178.88 178.566 178.066 177.827 177.564 177.378
 177.255 177.116 177.037 176.952 176.905 176.862  176.82 176.841 176.864 176.951
 176.973 177.036 177.164 177.226 177.303 177.431 177.448 177.496 177.544 177.592
 177.607 177.647 177.688 177.695 177.705 177.775 177.875 177.955 178.152 178.172
 178.325 178.364
       0      47     101     143     187     234     279     308     334     369
     405     428     484     486     507     526     557     578     599     620
     642     664     689     710     734     762     787     813     839     974
    1019    1065 1083.45 1104.65 1123.67 1142.94 1176.94 1199.82 1225.25    1251
 1267.33 1288.33 1305.41 1325.79    1332  1348.7 1381.56 1400.97 1447.82 1468.22
 1475.88 1488.341520.762 1533.511546.443 1565.65 1572.071591.275 1597.73 1604.19
 1616.83 1624.281631.7241637.273 1649.21 1662.05 1674.78 1687.39    1711 1721.69
 1745.221766.069    1829    1943    2036    2165    2365
     215     214     213     212     211     210     209 208.497  207.87 207.048
 205.965 205.336 203.447     203     202     201     200     199     198     197
     196     195     194     193     192     191     190     189     188     185
     184 183.136 182.811 182.456 182.175 181.861 181.361 181.122 180.859 180.673
  180.55 180.411 180.332 180.247   180.2 180.157 180.115 180.136 180.159 180.246
 180.268 180.331 180.459 180.521 180.598 180.726 180.743 180.791 180.839 180.887
 180.902 180.942 180.983  180.99     181  181.07  181.17  181.25 181.447 181.467
  181.62 181.659     182     183     184     185     186
                                                                                
                                                                                
                                                                                
         179.841 179.516 179.161  178.88 178.566 178.066 177.827 177.564 177.378
 177.255 177.116 177.037 176.952 176.905 176.862  176.82 176.841 176.864 176.951
 176.973 177.036 177.164 177.226 177.303 177.431 177.448 177.496 177.544 177.592
 177.607 177.647 177.688 177.695 177.705 177.775 177.875 177.955 178.152 178.172
 178.325 178.364
Pier Skew, UpSta & Num, DnSta & Num=  ,1135, 2 ,1135, 2 , 0 , 0 , 0 ,,
   5.425       4
   144.2   178.4
   5.425       4
   144.2   178.4
Pier Skew, UpSta & Num, DnSta & Num=  ,1205, 2 ,1205, 2 , 0 , 0 , 0 ,,
   5.425       4
   144.2   178.4
   5.425       4
   144.2   178.4
Pier Skew, UpSta & Num, DnSta & Num=  ,1275, 2 ,1275, 2 , 0 , 0 , 0 ,,
   5.425       4
   144.2   178.4
   5.425       4
   144.2   178.4
Pier Skew, UpSta & Num, DnSta & Num=  ,1345, 2 ,1345, 2 , 0 , 0 , 0 ,,
   5.425       4
   144.2   178.4
   5.425       4
   144.2   178.4
Pier Skew, UpSta & Num, DnSta & Num=  ,1415, 2 ,1415, 2 , 0 , 0 , 0 ,,
   5.425       4
   144.2   178.4
   5.425       4
   144.2   178.4
Pier Skew, UpSta & Num, DnSta & Num=  ,1485, 2 ,1485, 2 , 0 , 0 , 0 ,,
   5.425       4
   144.2   178.4
   5.425       4
   144.2   178.4
Pier Skew, UpSta & Num, DnSta & Num=  ,1555, 2 ,1555, 2 , 0 , 0 , 0 ,,
   5.425       4
   144.2   178.4
   5.425       4
   144.2   178.4
Pier Skew, UpSta & Num, DnSta & Num=  ,1625, 2 ,1625, 2 , 0 , 0 , 0 ,,
    5.33    5.33
   144.2   178.4
    5.33    5.33
   144.2   178.4
Pier Skew, UpSta & Num, DnSta & Num=  ,1695, 2 ,1695, 2 , 0 , 0 , 0 ,,
   5.425       4
   144.2   178.4
   5.425       4
   144.2   178.4
Abutment Skew #Up #Dn= , 3 , 3
    1065    1080    1120
  177.84  177.84  157.84
    1065    1080    1120
  177.84  177.84  157.84
Abutment Skew #Up #Dn= , 3 , 3
1711.0691751.0691766.069
 156.364 176.364 176.364
1711.0691751.0691766.069
 156.364 176.364 176.364
BR Coef= 1 , 0 , 1 ,1.25, 0 ,,,1.25,0,,0,176.82
WSPro=,,,, 1 ,,,, 0 ,,,, 0 ,,,,-1 ,-1 ,-1 , 0 , 0 , 0 , 0 , 0
BR D #Sta/Elev= 72
       0     195      22     194      47     193      74     192      99     191
     120     190     138     189     153     188     164     187     178     186
     191     185     210     184     237     183     245     182     251     181
     256     180     261     179     272     178     289     178     296     179
     306     180     329     179     349     178     392     178     398     179
     405   180.5     411     179     414     178     416     177     418     176
     420     175     423     174     425     173     448     172     465     171
     484     170     519     169     551   168.3     616   168.3     855     169
    1002     170    1025     171    1048     178    1053     179    1065     179
    1098     170    1117     169    1153     168    1219     167    1248     166
    1265     165    1276     162  1410.8  148.22  1480.8  148.22  1545.6  143.42
    1684     162    1690     163    1697     164    1701     165    1704     166
    1709     167    1714     168    1718     169    1722     170    1739     175
    1760     179    1777     180    1889     181    1962     182    2057     183
    2162     184    2288     185
BR D #Mann= 3
       0    .065    1153     .05    1714    .065
BR D Banks=1153,1714
BC Design=,, 0 ,, 0 ,,,,,,
BC Use User HTab Curves=0
BC User HTab FreeFlow(D)= 0

Type RM Length L Ch R = 1 ,17586   ,586,586,586
#Sta/Elev= 30
       0     190      68     185     138     181     161     179     165     178
     191   180.5     199     179     245     174     325     175     332     172
     343   169.7   401.4   169.7     508     167     788     166     842     165
     857     162     897     149     967     149    1047   144.2    1078     162
    1093     165    1105     166    1156     165    1158     166    1212     168
    1221     169    1244     175    1288     190    1306     195    1359     205
#Mann= 3 , 0 , 0
       0    .065       0     842     .05       0    1105    .065       0
#XS Ineff= 2 , 0
       0     841 180.115    1973       0 180.115
Permanent Ineff=
       F       F
Bank Sta=842,1105
XS Rating Curve= 0 ,0
Exp/Cntr=0.5,0.3

Type RM Length L Ch R = 1 ,17000   ,1900,1700,1500
BEGIN DESCRIPTION:
FEMA XS: G
END DESCRIPTION:
#Sta/Elev= 30
       0  224.22     475  199.22     700  189.22     800  184.22     915  179.02
     932  170.72    1000  171.82    1010  171.82    1028  168.02    1100  167.02
    1200  167.02    1300  167.52    1355  170.52    1385  170.12    1400  162.72
    1405  157.72    1425  147.82    1515  147.62    1595  149.62    1695  156.72
    1698  166.02    1748  166.52    1755  159.72    1775  160.82    1785  166.02
    1800  166.42    1855  166.32    1900  174.92    2000  199.22    2370  224.22
#Mann= 3 , 0 , 0
       0    .065       0    1400     .05       0    1698    .065       0
Bank Sta=1400,1698
XS Rating Curve= 0 ,0
Exp/Cntr=0.5,0.3

Type RM Length L Ch R = 1 ,15300   ,1500,1700,2100
BEGIN DESCRIPTION:
FEMA XS: F
END DESCRIPTION:
#Sta/Elev= 30
      30  224.22     350  199.22     550  189.22     750  174.22     800  169.22
     910  169.22    1000  181.52    1035  181.72    1238  172.42    1252  173.32
    1425  160.32    1435  157.72    1440  154.22    1475  149.92    1525  152.42
    1675  149.92    1755  152.32    1815  150.52    1818  158.72    1845  161.92
    1855  161.72    1865  155.72    1890  154.72    1920  155.22    1925  159.42
    2000  163.42    2215  172.32    2230  174.22    2290  199.22    2370  224.22
#Mann= 3 , 0 , 0
      30    .065       0    1435     .05       0    1925    .065       0
Bank Sta=1435,1925
XS Rating Curve= 0 ,0
Exp/Cntr=0.3,0.1

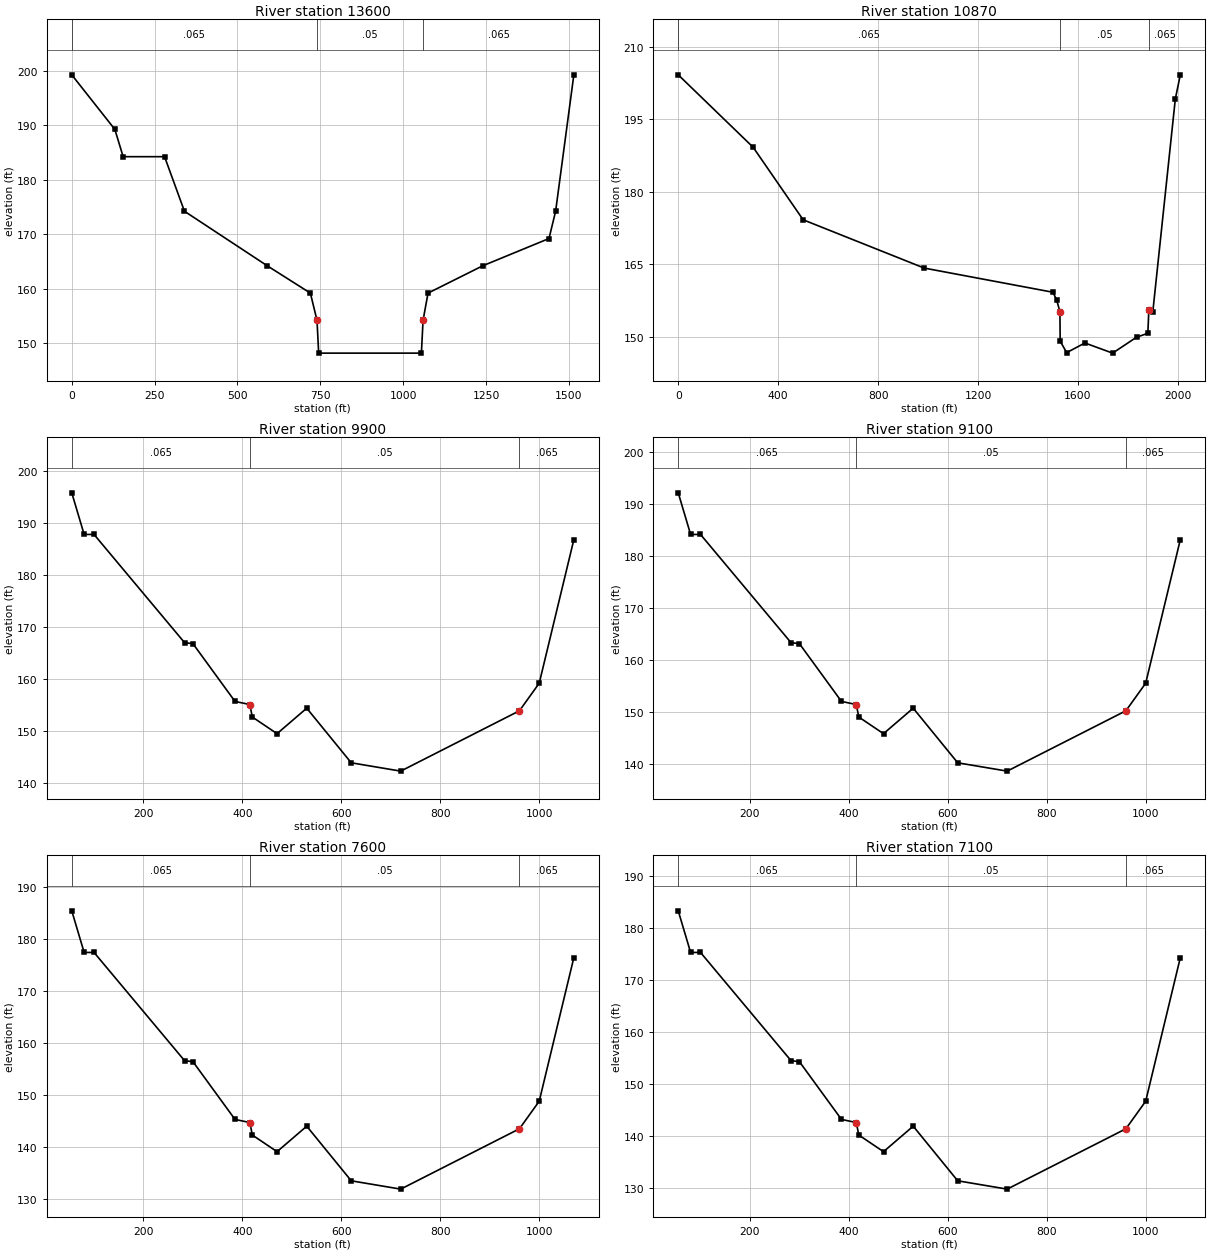
Type RM Length L Ch R = 1 ,13600   ,2400,2730,3000
BEGIN DESCRIPTION:
FEMA XS: E
END DESCRIPTION:
#Sta/Elev= 16
       0  199.22     130  189.22     155  184.22     280  184.22     340  174.22
     590  164.22     720  159.22     740  154.22     745  148.22    1055  148.22
    1060  154.22    1075  159.22    1240  164.22    1440  169.22    1460  174.22
    1515  199.22
#Mann= 3 , 0 , 0
       0    .065       0     740     .05       0    1060    .065       0
Bank Sta=740,1060
XS Rating Curve= 0 ,0
Exp/Cntr=0.3,0.1

Type RM Length L Ch R = 1 ,10870   ,1250,970,750
BEGIN DESCRIPTION:
FEMA XS: D
END DESCRIPTION:
#Sta/Elev= 17
       0  204.22     300  189.22     500  174.22     985  164.22    1500  159.22
    1515  157.62    1528  155.22    1529  149.12    1555  146.72    1628  148.72
    1739  146.62    1835  149.92    1880  150.72    1884  155.52    1900  155.22
    1990  199.22    2010  204.22
#Mann= 3 , 0 , 0
       0    .065       0    1528     .05       0    1884    .065       0
Bank Sta=1528,1884
XS Rating Curve= 0 ,0
Exp/Cntr=0.3,0.1

Type RM Length L Ch R = 1 ,9900    ,800,800,800
#Sta/Elev= 15
      55  195.72      80  187.72     100  187.72     283  166.92     300  166.72
     385  155.62     415  155.02     420  152.62     470  149.42     530  154.32
     620  143.82     720  142.22     960  153.82    1000  159.12    1070  186.72
#Mann= 3 , 0 , 0
      55    .065       0     415     .05       0     960    .065       0
Bank Sta=415,960
XS Rating Curve= 0 ,0
Exp/Cntr=0.3,0.1

Type RM Length L Ch R = 1 ,9100    ,1400,1500,1150
#Sta/Elev= 15
      55  192.12      80  184.12     100  184.12     283  163.32     300  163.12
     385  152.02     415  151.42     420  149.02     470  145.82     530  150.72
     620  140.22     720  138.62     960  150.22    1000  155.52    1070  183.12
#Mann= 3 , 0 , 0
      55    .065       0     415     .05       0     960    .065       0
Bank Sta=415,960
XS Rating Curve= 0 ,0
Exp/Cntr=0.3,0.1

Type RM Length L Ch R = 1 ,7600    ,450,500,500
#Sta/Elev= 15
      55  185.42      80  177.42     100  177.42     283  156.62     300  156.42
     385  145.32     415  144.72     420  142.32     470  139.12     530  144.02
     620  133.52     720  131.92     960  143.52    1000  148.82    1070  176.42
#Mann= 3 , 0 , 0
      55    .065       0     415     .05       0     960    .065       0
Bank Sta=415,960
XS Rating Curve= 0 ,0
Exp/Cntr=0.3,0.1

Type RM Length L Ch R = 1 ,7100    ,1950,2100,2200
BEGIN DESCRIPTION:
FEMA XS: C
END DESCRIPTION:
#Sta/Elev= 15
      55  183.22      80  175.22     100  175.22     283  154.42     300  154.22
     385  143.12     415  142.52     420  140.12     470  136.92     530  141.82
     620  131.32     720  129.72     960  141.32    1000  146.62    1070  174.22
#Mann= 3 , 0 , 0
      55    .065       0     415     .05       0     960    .065       0
Bank Sta=415,960
XS Rating Curve= 0 ,0
Exp/Cntr=0.3,0.1

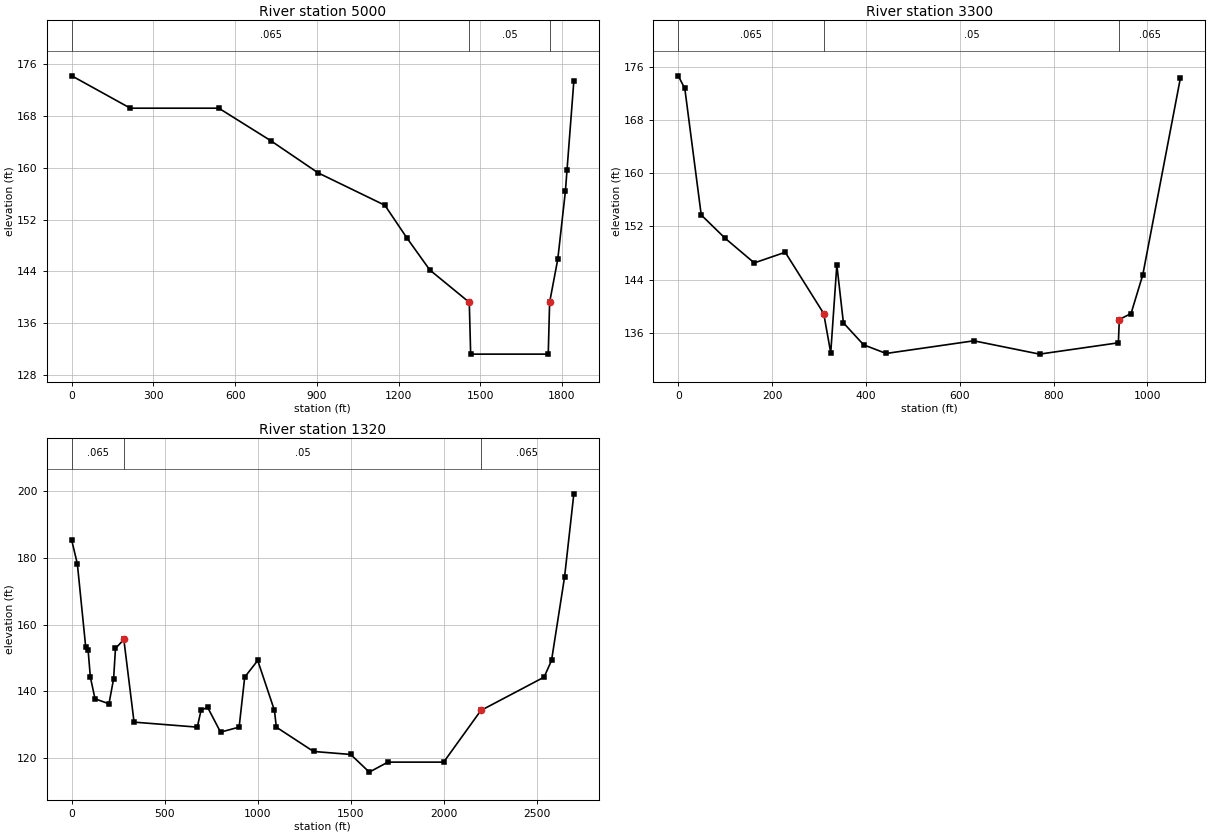
Type RM Length L Ch R = 1 ,5000    ,1700,1700,1700
BEGIN DESCRIPTION:
FEMA XS: B
END DESCRIPTION:
#Sta/Elev= 16
       0  174.22     215  169.22     540  169.22     730  164.22     905  159.22
    1150  154.22    1230  149.22    1315  144.22    1460  139.22    1465  131.22
    1750  131.22    1755  139.22    1785  145.89    1813   156.4    1819  159.72
    1844  173.41
#Mann= 3 , 0 , 0
       0    .065       0    1460     .05       0    1755    .065       0
Bank Sta=1460,1755
XS Rating Curve= 0 ,0
Exp/Cntr=0.3,0.1

Type RM Length L Ch R = 1 ,3300    ,2400,1980,2400
BEGIN DESCRIPTION:
FEMA XS: A
END DESCRIPTION:
#Sta/Elev= 19
       0  174.62      14  172.72      49  153.72     100  150.22     162  146.52
     228  148.12     310  138.92     325  133.02     338  146.22     352  137.52
     395  134.22     443  132.92     630  134.82     770  132.82     938  134.52
     940  138.02     965  138.92     990  144.72    1070  174.22
#Mann= 3 , 0 , 0
       0    .065       0     310     .05       0     940    .065       0
Bank Sta=310,940
XS Rating Curve= 0 ,0
Exp/Cntr=0.3,0.1

Type RM Length L Ch R = 1 ,1320    ,,,
BEGIN DESCRIPTION:
BEGIN
END DESCRIPTION:
#Sta/Elev= 30
       0  185.22      30  178.22      75  153.22      88  152.22     100  144.22
     125  137.72     200  136.22     225  143.72     235  152.82     280  155.52
     335  130.72     675  129.22     695  134.22     730  135.22     800  127.72
     900  129.22     930  144.22    1000  149.22    1090  134.22    1100  129.22
    1300  121.92    1500  121.02    1600  115.72    1700  118.72    2000  118.72
    2200  134.22    2540  144.22    2580  149.22    2650  174.22    2700  199.22
#Mann= 3 , 0 , 0
       0    .065       0     280     .05       0    2200    .065       0
#XS Ineff= 2 , 0
       0     280  155.42               0
Permanent Ineff=
       F       F
Bank Sta=280,2200
XS Rating Curve= 0 ,0
Exp/Cntr=0.3,0.1
LCMann Table=0

Chan Stop Cuts=-1
Use User Specified Reach Order=0
Composite Channel Slope=5

--- CCR_Saluda.g01 (geometry) ---

Geom Title=CCR_Effective_Saluda
Program Version=5.03

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
River Reach=Saluda River    ,Saluda River

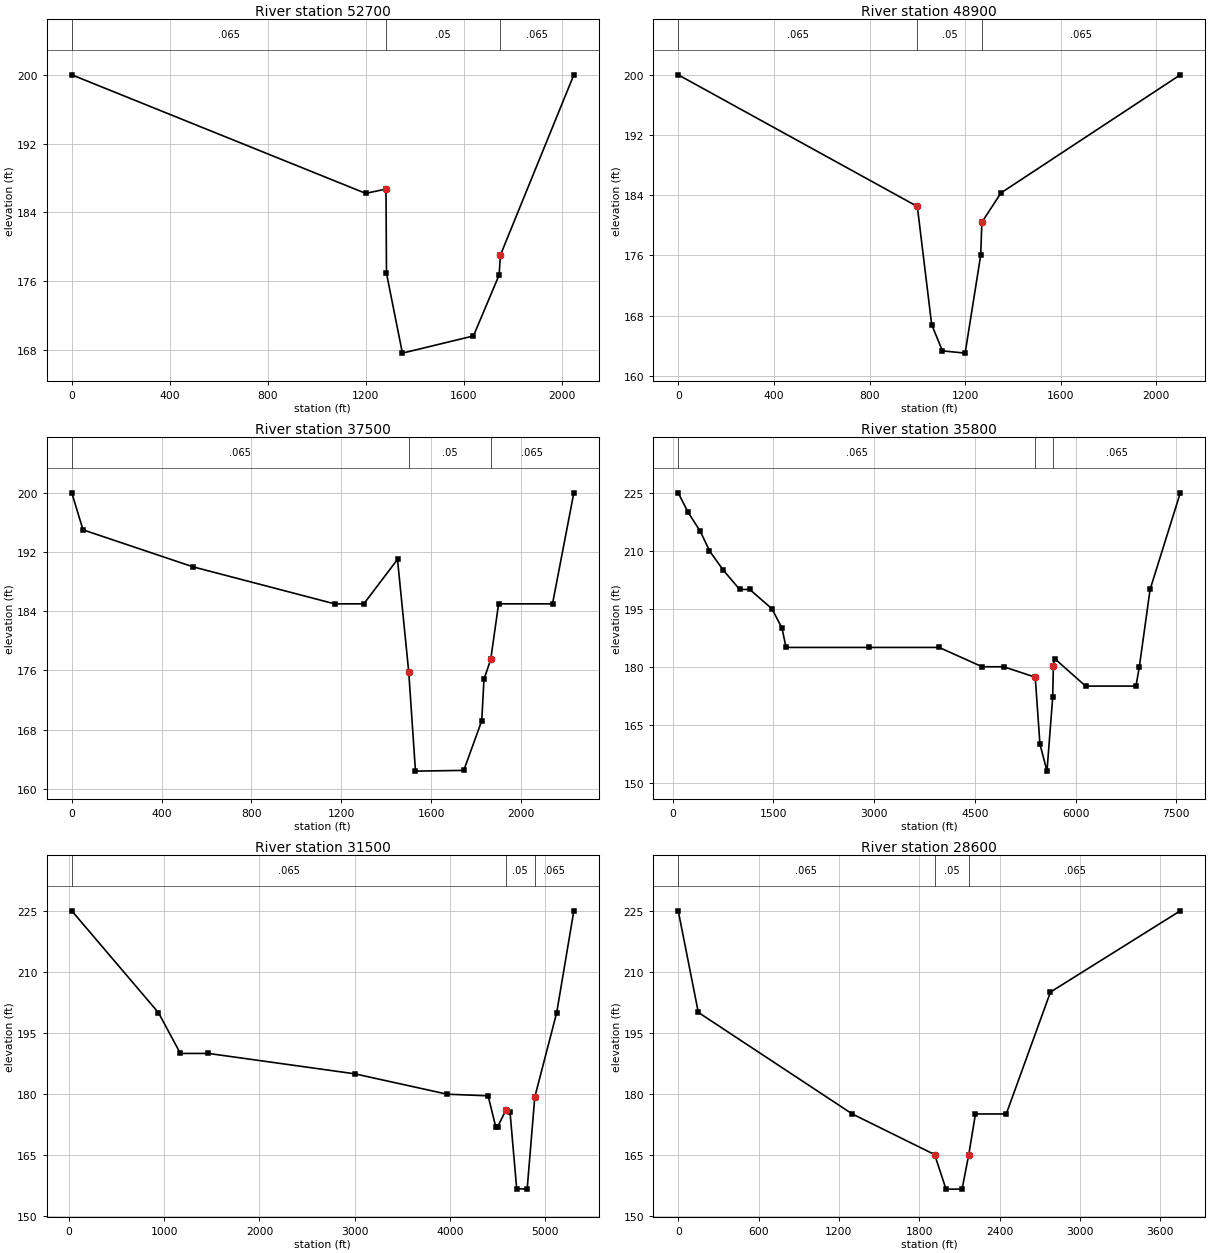
Type RM Length L Ch R = 1 ,52700   ,3800,3800,3800
BEGIN DESCRIPTION:
END
END DESCRIPTION:
#Sta/Elev= 9
       0     200    1200   186.2    1283   186.7    1285   176.9    1350   167.6
    1640   169.6    1745   176.7    1750     179    2050     200
#Mann= 3 , 0 , 0
       0    .065       0    1283     .05       0    1750    .065       0
Bank Sta=1283,1750
XS Rating Curve= 0 ,0
Exp/Cntr=0.3,0.1

Type RM Length L Ch R = 1 ,48900   ,11400,11400,11400
#Sta/Elev= 9
       0     200    1000   182.5    1060   166.8    1105   163.3    1200     163
    1265     176    1270   180.4    1350   184.3    2100     200
#Mann= 3 , 0 , 0
       0    .065       0    1000     .05       0    1270    .065       0
Bank Sta=1000,1270
XS Rating Curve= 0 ,0
Exp/Cntr=0.3,0.1

Type RM Length L Ch R = 1 ,37500   ,1700,1700,1700
BEGIN DESCRIPTION:
FEMA XS: O
END DESCRIPTION:
#Sta/Elev= 15
       0     200      50     195     540     190    1170     185    1300     185
    1450     191    1500   175.8    1530   162.4    1745   162.5    1825   169.2
    1835   174.8    1865   177.5    1900     185    2140     185    2235     200
#Mann= 3 , 0 , 0
       0    .065       0    1500     .05       0    1865    .065       0
Bank Sta=1500,1865
XS Rating Curve= 0 ,0
Exp/Cntr=0.3,0.1

Type RM Length L Ch R = 1 ,35800   ,4100,4300,4400
BEGIN DESCRIPTION:
FEMA XS: N
END DESCRIPTION:
#Sta/Elev= 25
      85     225     230     220     415     215     550     210     755     205
    1000     200    1150     200    1480     195    1630     190    1690     185
    2930     185    3970     185    4610     180    4930     180    5400   177.3
    5470     160    5575     153    5660   172.1    5670   180.2    5690   182.1
    6150     175    6900     175    6950     180    7110     200    7560     225
#Mann= 3 , 0 , 0
      85    .065       0    5400     .05       0    5670    .065       0
Bank Sta=5400,5670
XS Rating Curve= 0 ,0
Exp/Cntr=0.3,0.1

Type RM Length L Ch R = 1 ,31500   ,2900,2900,2900
BEGIN DESCRIPTION:
FEMA XS: M
END DESCRIPTION:
#Sta/Elev= 16
      30     225     940     200    1170     190    1465     190    3000     185
    3970     180    4400   179.6    4480     172    4500     172    4585     176
    4630   175.6    4700   156.8    4810   156.7    4890   179.3    5120     200
    5300     225
#Mann= 3 , 0 , 0
      30    .065       0    4585     .05       0    4890    .065       0
Bank Sta=4585,4890
XS Rating Curve= 0 ,0
Exp/Cntr=0.3,0.1

Type RM Length L Ch R = 1 ,28600   ,2600,2600,2600
BEGIN DESCRIPTION:
FEMA XS: L
END DESCRIPTION:
#Sta/Elev= 11
       0     225     150     200    1300     175    1915     165    2000   156.5
    2120   156.5    2170     165    2220     175    2450     175    2780     205
    3750     225
#Mann= 3 , 0 , 0
       0    .065       0    1915     .05       0    2170    .065       0
Bank Sta=1915,2170
XS Rating Curve= 0 ,0
Exp/Cntr=0.3,0.1