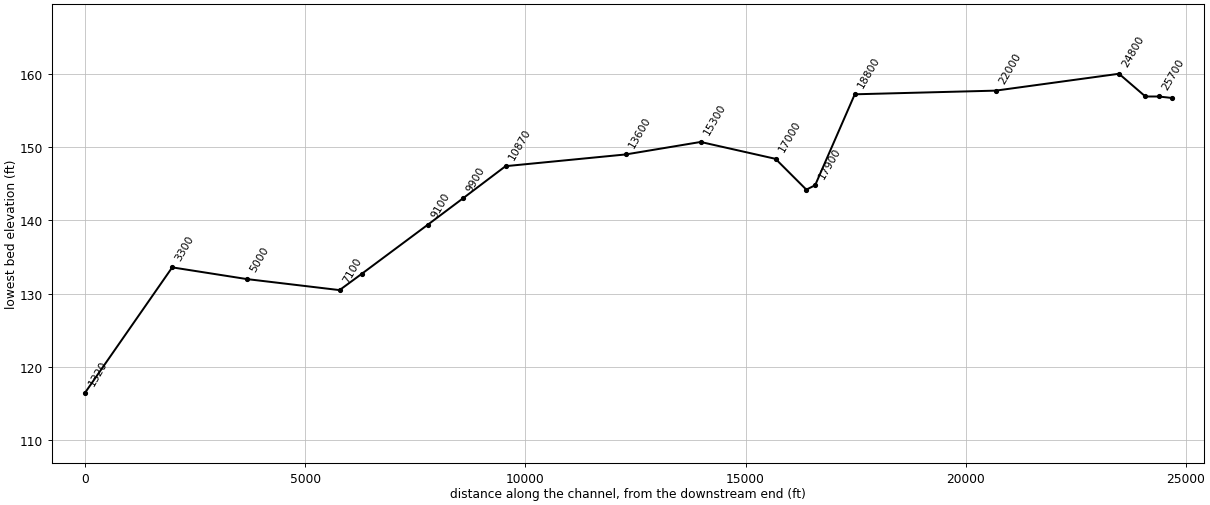
HEC-RAS study CCR_Saluda.prj: CCR_Saluda

--- CCR_Saluda.g01 (geometry) --- (continued)

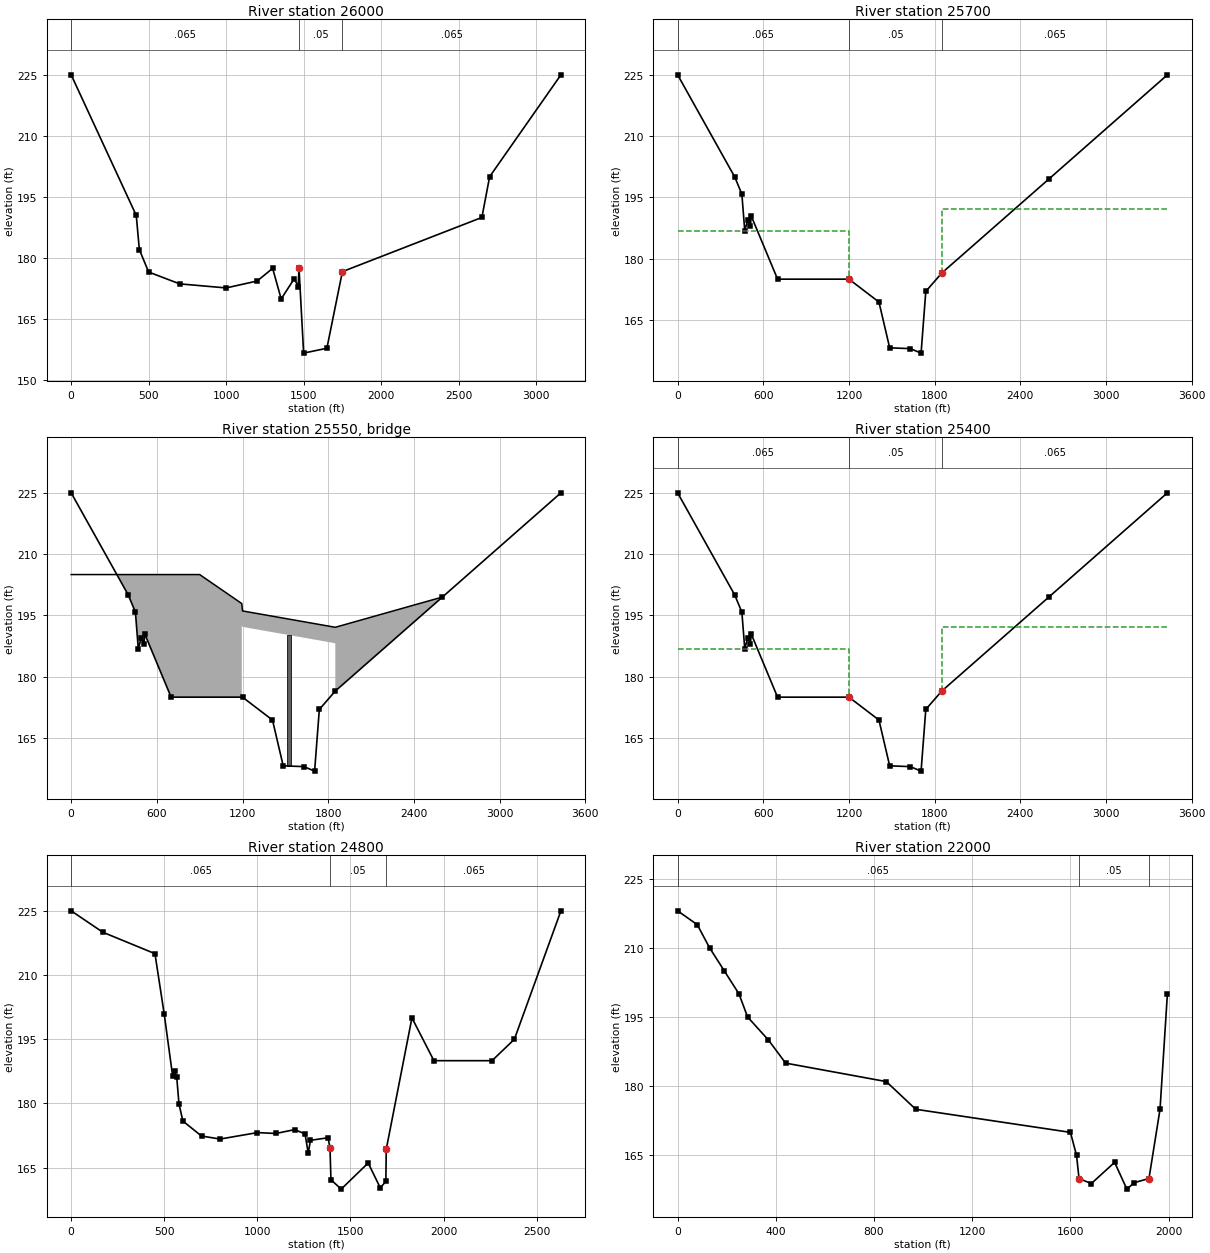
Type RM Length L Ch R = 1 ,26000   ,400,300,250
BEGIN DESCRIPTION:
FEMA XS: K
END DESCRIPTION:
#Sta/Elev= 18
       0     225     420   190.5     440   182.1     500   176.6     700   173.7
    1000   172.7    1200   174.4    1300   177.5    1355     170    1440     175
    1465     173    1470   177.6    1500   156.7    1650   157.9    1750   176.7
    2650     190    2700     200    3160     225
#Mann= 3 , 0 , 0
       0    .065       0    1470     .05       0    1750    .065       0
Bank Sta=1470,1750
XS Rating Curve= 0 ,0
Exp/Cntr=0.3,0.1

Type RM Length L Ch R = 1 ,25700   ,300,300,300
#Sta/Elev= 17
       0     225     400     200     450   195.8     470   186.9     492   189.5
     510     188     515   190.5     700     175    1200     175    1410   169.4
    1485   158.2    1630     158    1705   156.9    1738     172    1850   176.5
    2600   199.5    3430     225
#Mann= 3 , 0 , 0
       0    .065       0    1200     .05       0    1850    .065       0
#XS Ineff= 2 , 0
       0    1200   186.9    1850       0   192.1
Permanent Ineff=
       F       F
Bank Sta=1200,1850
XS Rating Curve= 0 ,0
Exp/Cntr=0.3,0.1

Type RM Length L Ch R = 3 ,25550   ,,,
Bridge Culvert--1,0,-1,-1, 0
Deck Dist Width WeirC Skew NumUp NumDn MinLoCord MaxHiCord MaxSubmerge Is_Ogee
0.25,299.5,2.5,0, 8, 8, 192.1, , 0.98, 0, 5.8,5.8,,
       0     900    1195    1195    1200    1850    1850    2600
     205     205   197.9   197.9   196.1   192.1   192.1   199.5
                           192.5   192.2   188.2
       0     900    1195    1195    1200    1850    1850    2600
     205     205   197.9   197.9   196.1   192.1   192.1   199.5
                           192.5   192.2   188.2
Pier Skew, UpSta & Num, DnSta & Num=  ,1525, 2 ,1525, 2 , 0 , 0 , 0 ,,
      32      32
   156.9   192.2
      32      32
   156.9   192.2
BR Coef= 0 , 0 , 1 ,1.25, 0 ,,,1.3,0,,2,192.2
WSPro=,,,, 1 ,,,, 0 ,,,, 0 ,,,,-1 ,-1 ,-1 , 0 , 0 , 0 , 0 , 0
BC Design=,, 0 ,, 0 ,,,,,,
BC Use User HTab Curves=0
BC User HTab FreeFlow(D)= 0

Type RM Length L Ch R = 1 ,25400   ,500,600,600
#Sta/Elev= 17
       0     225     400     200     450   195.8     470   186.9     492   189.5
     510     188     515   190.5     700     175    1200     175    1410   169.4
    1485   158.2    1630     158    1705   156.9    1738     172    1850   176.5
    2600   199.5    3430     225
#Mann= 3 , 0 , 0
       0    .065       0    1200     .05       0    1850    .065       0
#XS Ineff= 2 , 0
       0    1200   186.9    1850       0   192.1
Permanent Ineff=
       F       F
Bank Sta=1200,1850
XS Rating Curve= 0 ,0
Exp/Cntr=0.3,0.1

Type RM Length L Ch R = 1 ,24800   ,2800,2800,2800
BEGIN DESCRIPTION:
FEMA XS: J
END DESCRIPTION:
#Sta/Elev= 30
       0     225     170     220     450     215     500   200.8     545   186.4
     555   187.6     567   186.1     579   179.9     600   175.9     700   172.4
     800   171.7    1000   173.2    1100     173    1200   173.9    1256   172.9
    1273   168.4    1285   171.4    1380     172    1390   169.5    1395   162.2
    1450     160    1595   166.1    1660   160.3    1690   161.8    1692   169.3
    1830     200    1948     190    2260     190    2380     195    2630     225
#Mann= 3 , 0 , 0
       0    .065       0    1390     .05       0    1692    .065       0
Bank Sta=1390,1692
XS Rating Curve= 0 ,0
Exp/Cntr=0.3,0.1

Type RM Length L Ch R = 1 ,22000   ,3200,3200,3200
BEGIN DESCRIPTION:
FEMA XS: I
END DESCRIPTION:
#Sta/Elev= 20
       0     218      80     215     130     210     190     205     250     200
     285     195     370     190     440     185     850     181     970     175
    1600     170    1625     165    1635     160    1685   158.9    1780   163.5
    1830   157.7    1860   159.1    1920     160    1965     175    1995     200
#Mann= 3 , 0 , 0
       0    .065       0    1635     .05       0    1920    .065       0
Bank Sta=1635,1920
XS Rating Curve= 0 ,0
Exp/Cntr=0.3,0.1

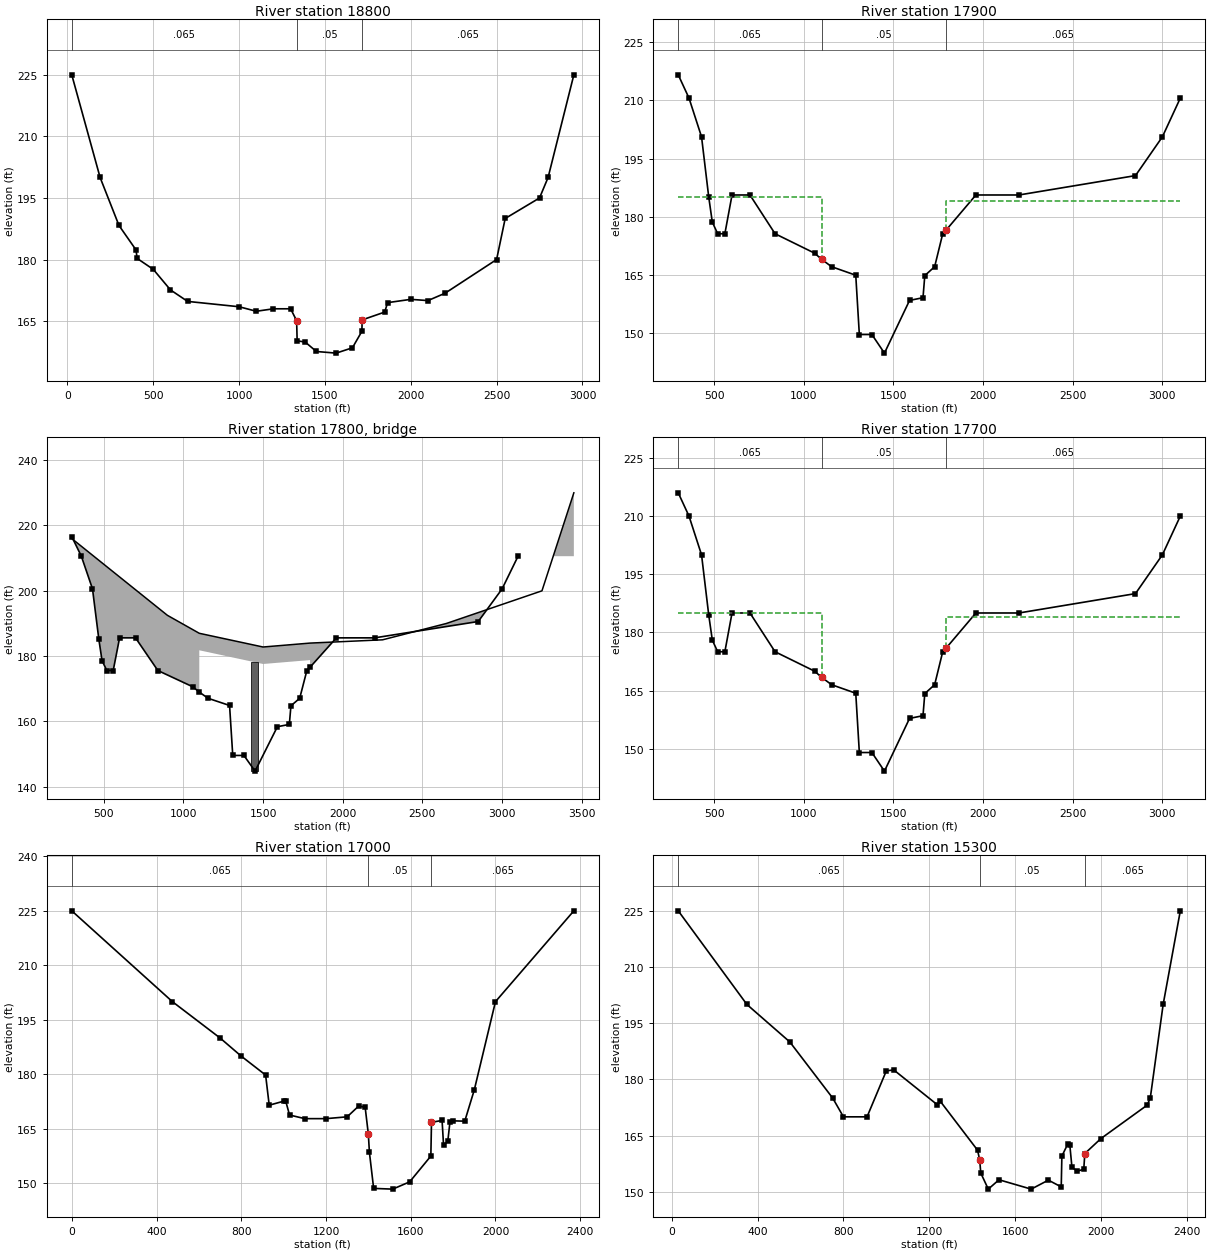
Type RM Length L Ch R = 1 ,18800   ,900,900,900
BEGIN DESCRIPTION:
FEMA XS: H
END DESCRIPTION:
#Sta/Elev= 30
      25     225     190     200     300   188.3     400   182.3     405   180.3
     500   177.6     600   172.6     700   169.8    1000   168.5    1100   167.4
    1200     168    1300     168    1335   165.1    1338   160.2    1385   159.9
    1450   157.6    1565   157.2    1660   158.5    1715   162.5    1717   165.3
    1848   167.2    1865   169.5    2000   170.3    2100     170    2200   171.8
    2500     180    2550     190    2750     195    2800     200    2950     225
#Mann= 3 , 0 , 0
      25    .065       0    1335     .05       0    1717    .065       0
Bank Sta=1335,1717
XS Rating Curve= 0 ,0
Exp/Cntr=0.3,0.1

Type RM Length L Ch R = 1 ,17900   ,200,200,200
#Sta/Elev= 28
     300   216.6     360   210.6     430   200.6     470   185.1     490   178.6
     520   175.6     560   175.6     600   185.6     700   185.6     840   175.6
    1060   170.6    1100     169    1155   167.1    1290   164.9    1310   149.6
    1380   149.6    1450   144.8    1590   158.4    1665   159.1    1675   164.8
    1730   167.1    1775   175.6    1795   176.6    1960   185.6    2200   185.6
    2850   190.6    3000   200.6    3100   210.6
#Mann= 3 , 0 , 0
     300    .065       0    1100     .05       0    1795    .065       0
#XS Ineff= 2 , 0
       0    1100     185    1795       0     184
Permanent Ineff=
       F       F
Bank Sta=1100,1795
XS Rating Curve= 0 ,0
Exp/Cntr=0.3,0.1

Type RM Length L Ch R = 3 ,17800   ,,,
Bridge Culvert--1,0,-1,-1, 0
Deck Dist Width WeirC Skew NumUp NumDn MinLoCord MaxHiCord MaxSubmerge Is_Ogee
0.25,199.5,2.5,0, 11, 11, 182.8, , 0.98, 0, 7.5,7.5,,
     300     900    1100    1100    1500    1795    1795    2250    2650    3250
    3450
     216   192.5     187     187   182.8     184     184     185     190     200
     230
                           181.8   177.6   178.8
        
     300     900    1100    1100    1500    1795    1795    2250    2650    3250
    3450
     216   192.5     187     187   182.8     184     184     185     190     200
     230
                           181.8   177.6   178.8
        
Pier Skew, UpSta & Num, DnSta & Num=  ,1447.5, 2 ,1447.5, 2 , 0 , 0 , 0 ,,
      48      48
   144.2   178.4
      48      48
   144.2   178.4
BR Coef= 0 , 0 , 1 ,1.25, 0 ,,,1.25,0,,2,177.6
WSPro=,,,, 1 ,,,, 0 ,,,, 0 ,,,,-1 ,-1 ,-1 , 0 , 0 , 0 , 0 , 0
BC Design=,, 0 ,, 0 ,,,,,,
BC Use User HTab Curves=0
BC User HTab FreeFlow(D)= 0

Type RM Length L Ch R = 1 ,17700   ,700,700,700
#Sta/Elev= 28
     300     216     360     210     430     200     470   184.5     490     178
     520     175     560     175     600     185     700     185     840     175
    1060     170    1100   168.4    1155   166.5    1290   164.3    1310     149
    1380     149    1450   144.2    1590   157.8    1665   158.5    1675   164.2
    1730   166.5    1775     175    1795     176    1960     185    2200     185
    2850     190    3000     200    3100     210
#Mann= 3 , 0 , 0
     300    .065       0    1100     .05       0    1795    .065       0
#XS Ineff= 2 , 0
       0    1100     185    1795       0     184
Permanent Ineff=
       F       F
Bank Sta=1100,1795
XS Rating Curve= 0 ,0
Exp/Cntr=0.3,0.1

Type RM Length L Ch R = 1 ,17000   ,1900,1700,1500
BEGIN DESCRIPTION:
FEMA XS: G
END DESCRIPTION:
#Sta/Elev= 30
       0     225     475     200     700     190     800     185     915   179.8
     932   171.5    1000   172.6    1010   172.6    1028   168.8    1100   167.8
    1200   167.8    1300   168.3    1355   171.3    1385   170.9    1400   163.5
    1405   158.5    1425   148.6    1515   148.4    1595   150.4    1695   157.5
    1698   166.8    1748   167.3    1755   160.5    1775   161.6    1785   166.8
    1800   167.2    1855   167.1    1900   175.7    2000     200    2370     225
#Mann= 3 , 0 , 0
       0    .065       0    1400     .05       0    1698    .065       0
Bank Sta=1400,1698
XS Rating Curve= 0 ,0
Exp/Cntr=0.3,0.1

Type RM Length L Ch R = 1 ,15300   ,1500,1700,2100
BEGIN DESCRIPTION:
FEMA XS: F
END DESCRIPTION:
#Sta/Elev= 30
      30     225     350     200     550     190     750     175     800     170
     910     170    1000   182.3    1035   182.5    1238   173.2    1252   174.1
    1425   161.1    1435   158.5    1440     155    1475   150.7    1525   153.2
    1675   150.7    1755   153.1    1815   151.3    1818   159.5    1845   162.7
    1855   162.5    1865   156.5    1890   155.5    1920     156    1925   160.2
    2000   164.2    2215   173.1    2230     175    2290     200    2370     225
#Mann= 3 , 0 , 0
      30    .065       0    1435     .05       0    1925    .065       0
Bank Sta=1435,1925
XS Rating Curve= 0 ,0
Exp/Cntr=0.3,0.1

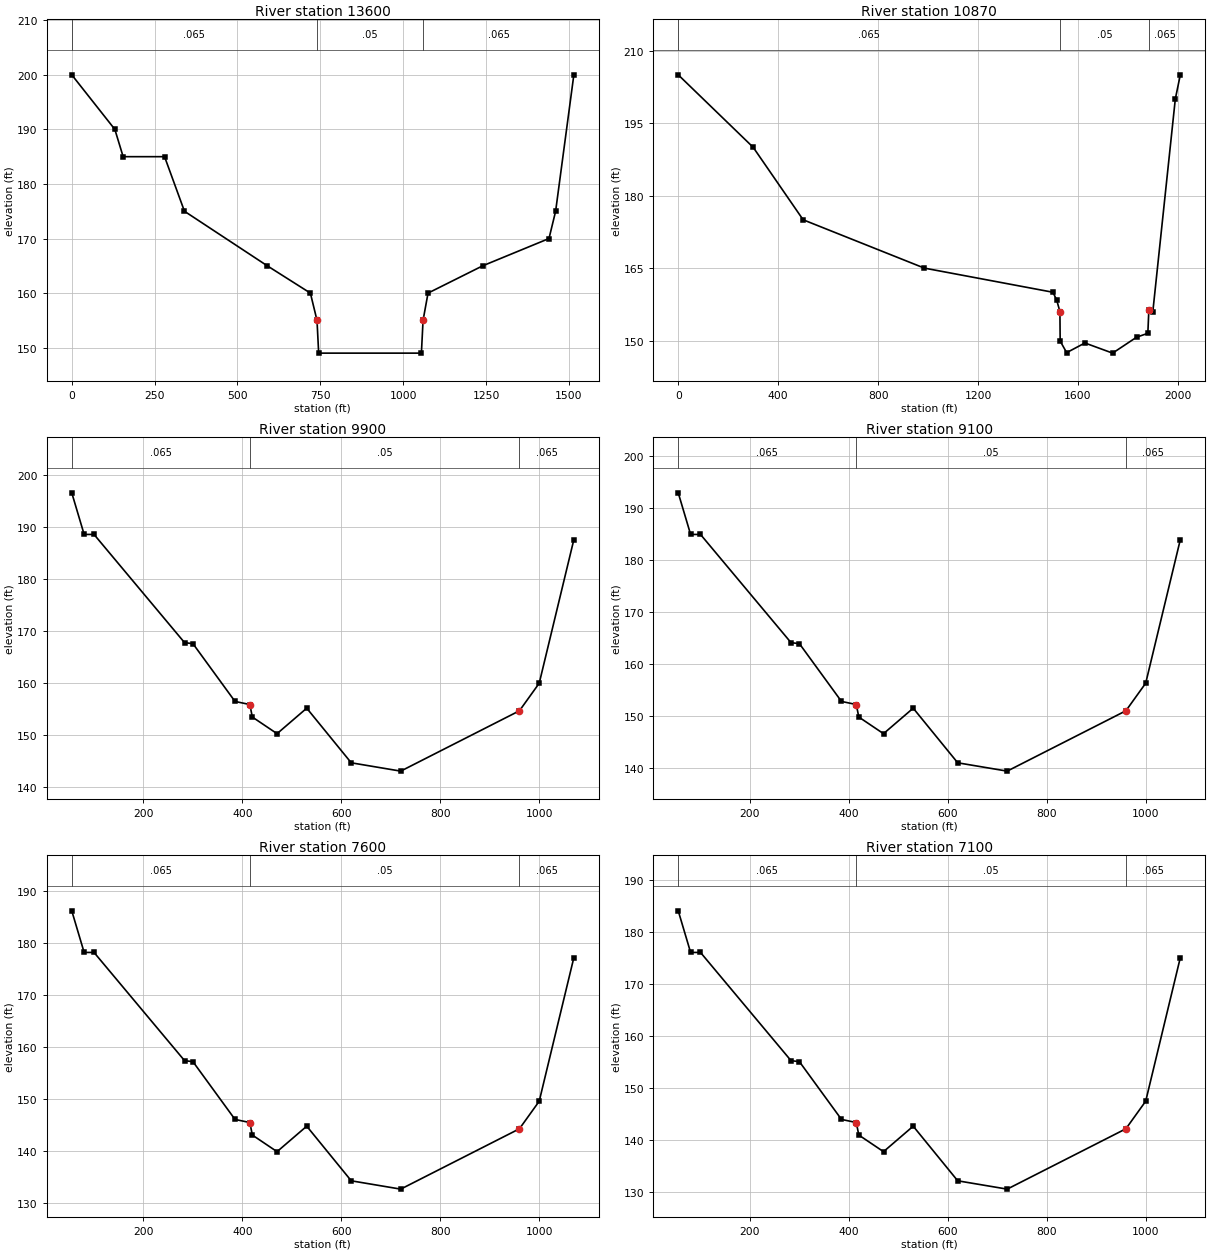
Type RM Length L Ch R = 1 ,13600   ,2400,2730,3000
BEGIN DESCRIPTION:
FEMA XS: E
END DESCRIPTION:
#Sta/Elev= 16
       0     200     130     190     155     185     280     185     340     175
     590     165     720     160     740     155     745     149    1055     149
    1060     155    1075     160    1240     165    1440     170    1460     175
    1515     200
#Mann= 3 , 0 , 0
       0    .065       0     740     .05       0    1060    .065       0
Bank Sta=740,1060
XS Rating Curve= 0 ,0
Exp/Cntr=0.3,0.1

Type RM Length L Ch R = 1 ,10870   ,1250,970,750
BEGIN DESCRIPTION:
FEMA XS: D
END DESCRIPTION:
#Sta/Elev= 17
       0     205     300     190     500     175     985     165    1500     160
    1515   158.4    1528     156    1529   149.9    1555   147.5    1628   149.5
    1739   147.4    1835   150.7    1880   151.5    1884   156.3    1900     156
    1990     200    2010     205
#Mann= 3 , 0 , 0
       0    .065       0    1528     .05       0    1884    .065       0
Bank Sta=1528,1884
XS Rating Curve= 0 ,0
Exp/Cntr=0.3,0.1

Type RM Length L Ch R = 1 ,9900    ,800,800,800
#Sta/Elev= 15
      55   196.5      80   188.5     100   188.5     283   167.7     300   167.5
     385   156.4     415   155.8     420   153.4     470   150.2     530   155.1
     620   144.6     720     143     960   154.6    1000   159.9    1070   187.5
#Mann= 3 , 0 , 0
      55    .065       0     415     .05       0     960    .065       0
Bank Sta=415,960
XS Rating Curve= 0 ,0
Exp/Cntr=0.3,0.1

Type RM Length L Ch R = 1 ,9100    ,1400,1500,1150
#Sta/Elev= 15
      55   192.9      80   184.9     100   184.9     283   164.1     300   163.9
     385   152.8     415   152.2     420   149.8     470   146.6     530   151.5
     620     141     720   139.4     960     151    1000   156.3    1070   183.9
#Mann= 3 , 0 , 0
      55    .065       0     415     .05       0     960    .065       0
Bank Sta=415,960
XS Rating Curve= 0 ,0
Exp/Cntr=0.3,0.1

Type RM Length L Ch R = 1 ,7600    ,450,500,500
#Sta/Elev= 15
      55   186.2      80   178.2     100   178.2     283   157.4     300   157.2
     385   146.1     415   145.5     420   143.1     470   139.9     530   144.8
     620   134.3     720   132.7     960   144.3    1000   149.6    1070   177.2
#Mann= 3 , 0 , 0
      55    .065       0     415     .05       0     960    .065       0
Bank Sta=415,960
XS Rating Curve= 0 ,0
Exp/Cntr=0.3,0.1

Type RM Length L Ch R = 1 ,7100    ,1950,2100,2200
BEGIN DESCRIPTION:
FEMA XS: C
END DESCRIPTION:
#Sta/Elev= 15
      55     184      80     176     100     176     283   155.2     300     155
     385   143.9     415   143.3     420   140.9     470   137.7     530   142.6
     620   132.1     720   130.5     960   142.1    1000   147.4    1070     175
#Mann= 3 , 0 , 0
      55    .065       0     415     .05       0     960    .065       0
Bank Sta=415,960
XS Rating Curve= 0 ,0
Exp/Cntr=0.3,0.1

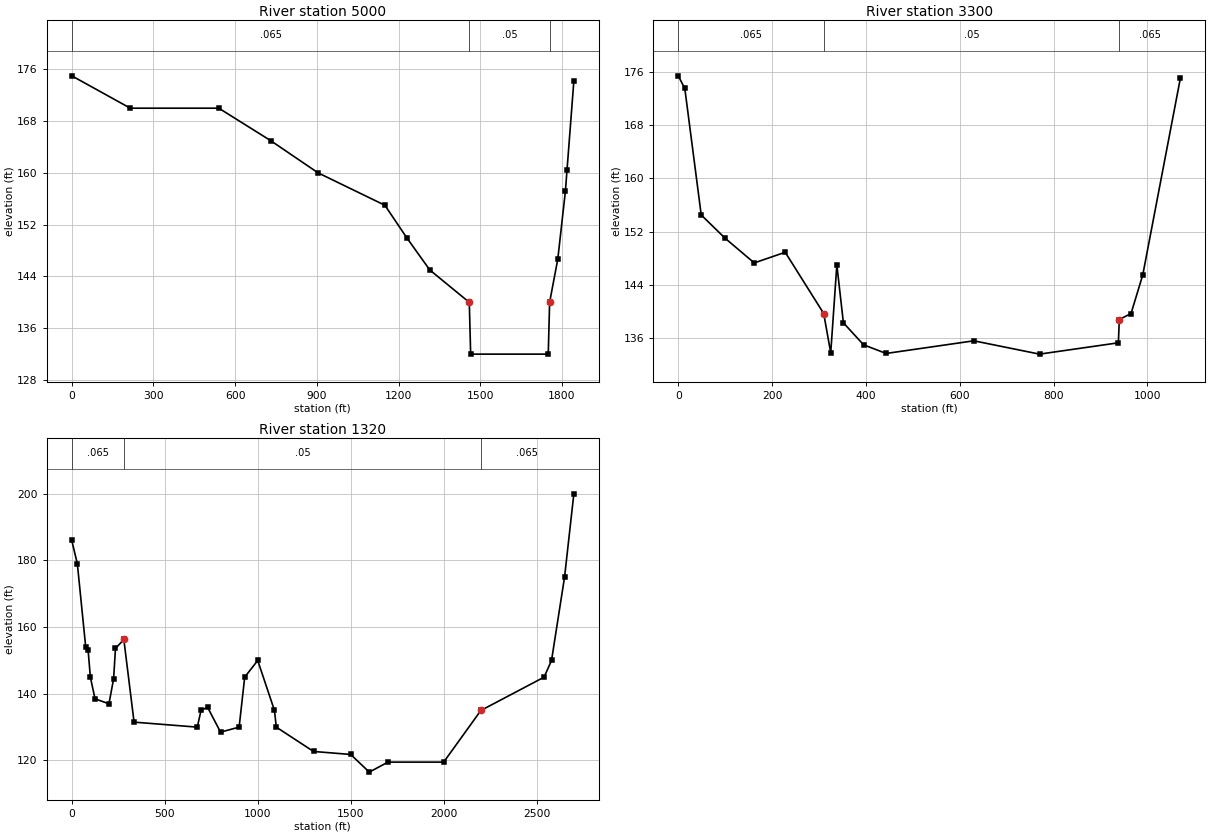
Type RM Length L Ch R = 1 ,5000    ,1700,1700,1700
BEGIN DESCRIPTION:
FEMA XS: B
END DESCRIPTION:
#Sta/Elev= 16
       0     175     215     170     540     170     730     165     905     160
    1150     155    1230     150    1315     145    1460     140    1465     132
    1750     132    1755     140    1785  146.67    1813  157.18    1819   160.5
    1844  174.19
#Mann= 3 , 0 , 0
       0    .065       0    1460     .05       0    1755    .065       0
Bank Sta=1460,1755
XS Rating Curve= 0 ,0
Exp/Cntr=0.3,0.1

Type RM Length L Ch R = 1 ,3300    ,2400,1980,2400
BEGIN DESCRIPTION:
FEMA XS: A
END DESCRIPTION:
#Sta/Elev= 19
       0   175.4      14   173.5      49   154.5     100     151     162   147.3
     228   148.9     310   139.7     325   133.8     338     147     352   138.3
     395     135     443   133.7     630   135.6     770   133.6     938   135.3
     940   138.8     965   139.7     990   145.5    1070     175
#Mann= 3 , 0 , 0
       0    .065       0     310     .05       0     940    .065       0
Bank Sta=310,940
XS Rating Curve= 0 ,0
Exp/Cntr=0.3,0.1

Type RM Length L Ch R = 1 ,1320    ,,,
BEGIN DESCRIPTION:
BEGIN
END DESCRIPTION:
#Sta/Elev= 30
       0     186      30     179      75     154      88     153     100     145
     125   138.5     200     137     225   144.5     235   153.6     280   156.3
     335   131.5     675     130     695     135     730     136     800   128.5
     900     130     930     145    1000     150    1090     135    1100     130
    1300   122.7    1500   121.8    1600   116.5    1700   119.5    2000   119.5
    2200     135    2540     145    2580     150    2650     175    2700     200
#Mann= 3 , 0 , 0
       0    .065       0     280     .05       0    2200    .065       0
#XS Ineff= 2 , 0
       0     280   156.2               0
Permanent Ineff=
       F       F
Bank Sta=280,2200
XS Rating Curve= 0 ,0
Exp/Cntr=0.3,0.1
LCMann Table=0